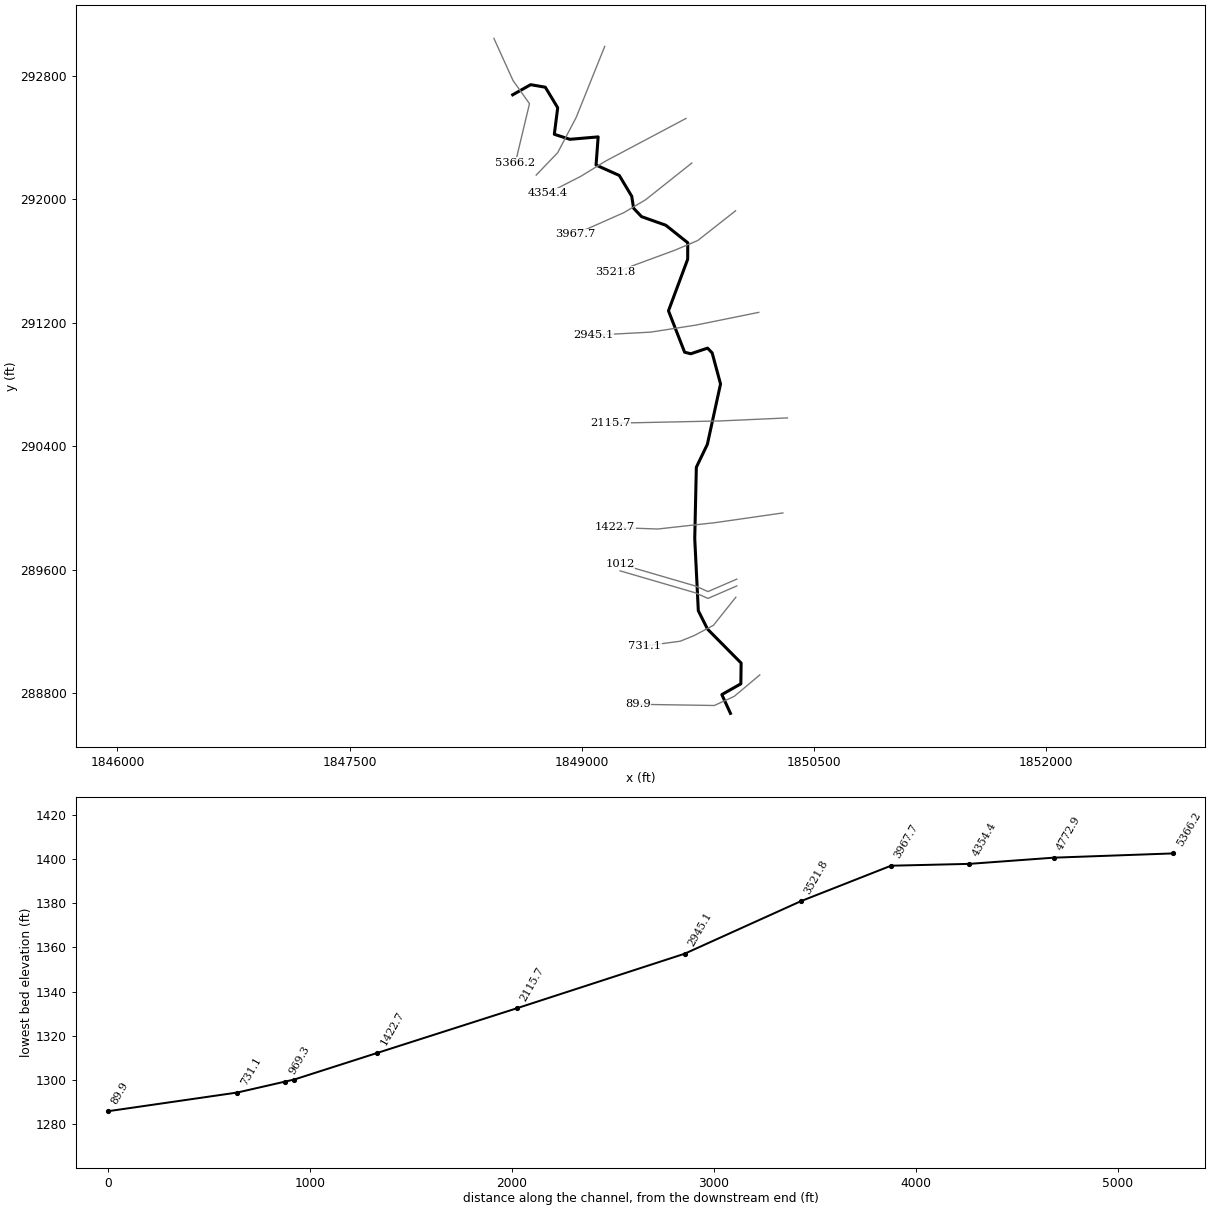
--- GladeRun.prj (project) ---

Proj Title=GladeRun
Current Plan=p01
Default Exp/Contr=0,0
English Units
Geom File=g01
Flow File=f01
Plan File=p01
BEGIN DESCRIPTION:
END DESCRIPTION:
DSS Export Rating Curves= 0
DSS Export Rating Curve Sorted= 0
DSS Export Volume Flow Curves= 0
DXF OffsetX= 0
DXF OffsetY= 0
DXF ScaleX= 0
DXF ScaleY= 0

--- GladeRun.p01 (plan) ---

Plan Title=Floodplain
Program Version=4.00
Geom File=g01
Flow File=f01
K Sum by GR=0
Std Step Tol=0.01
Critical Tol=0.01
Num of Std Step Trials=20
Max Error Tol=0.3
Flow Tol Ratio=0.001
Split Flow NTrial=30
Split Flow Tol=0.02
Split Flow Ratio=0.02
Log Output Level=0
Friction Slope Method=1
Unsteady Friction Slope Method=2
Unsteady Bridges Friction Slope Method=1
Global Log Level=0
CheckData=False
Run HTab=0
Run UNet=0
Run PostProcess=0
UNET Theta=0
UNET Theta Warmup=0
UNET ZTol=0
UNET ZSATol=0
UNET MxIter=0
UNET MaxInSteps=0
UNET DtIC=0
UNET DtMin=0
UNET MaxCRTS=0
UNET WFStab=0
UNET SFStab=0
UNET WFX=0
UNET SFX=0
UNET DSS MLevel=0
UNET DZMax Abort=0
UNET Convert EG Bridges=0
UNET Use Existing IB Tables=0
UNET Froude Limit=0
UNET Froude Power=0
Write IC File=0
Echo Input=False
Echo Output=False
Write Detailed=0

--- GladeRun.f01 (steady flow) ---

Flow Title=NFF Regression Equation
Program Version=4.10
Number of Profiles= 1
Profile Names=P100yr
River Rch & RM=GladeRun,Main            ,5366.2
     517
River Rch & RM=GladeRun,Main            ,4772.9
     540
River Rch & RM=GladeRun,Main            ,4354.4
     625
River Rch & RM=GladeRun,Main            ,89.9
     673
Boundary for River Rch & Prof#=GladeRun,Main            , 1
Up Type= 0
Dn Type= 3
Dn Slope=0.01322
DSS Import GetInterval= 0
DSS Import GetPeak= 0
DSS Import FillOption= 0

--- GladeRun.g01 (geometry) ---

Geom Title=USGS 10m DEM
Program Version=4.10

River Reach=GladeRun        ,Main
Reach XY= 30
     1848553.916      292675.168     1848669.959      292740.834
     1848764.722      292724.283     1848844.679      292591.408
     1848822.799      292419.506     1848923.045      292387.078
     1849106.013      292402.657     1849092.459      292220.335
     1849242.646      292152.959     1849322.907      292018.393
      1849334.97      291940.791     1849386.532      291886.294
     1849543.129      291830.696     1849684.988      291717.248
     1849684.384      291610.329     1849560.419      291276.536
     1849664.711      291008.477     1849704.408      290998.438
     1849813.059      291035.031      1849842.73       291003.76
     1849896.726      290802.899     1849811.679       290412.18
     1849740.447      290263.699     1849730.108      289801.216
     1849753.167      289334.803     1849812.803      289215.532
     1850029.819      288995.938     1850027.974      288861.425
     1849905.141      288791.708     1849960.915       288670.08

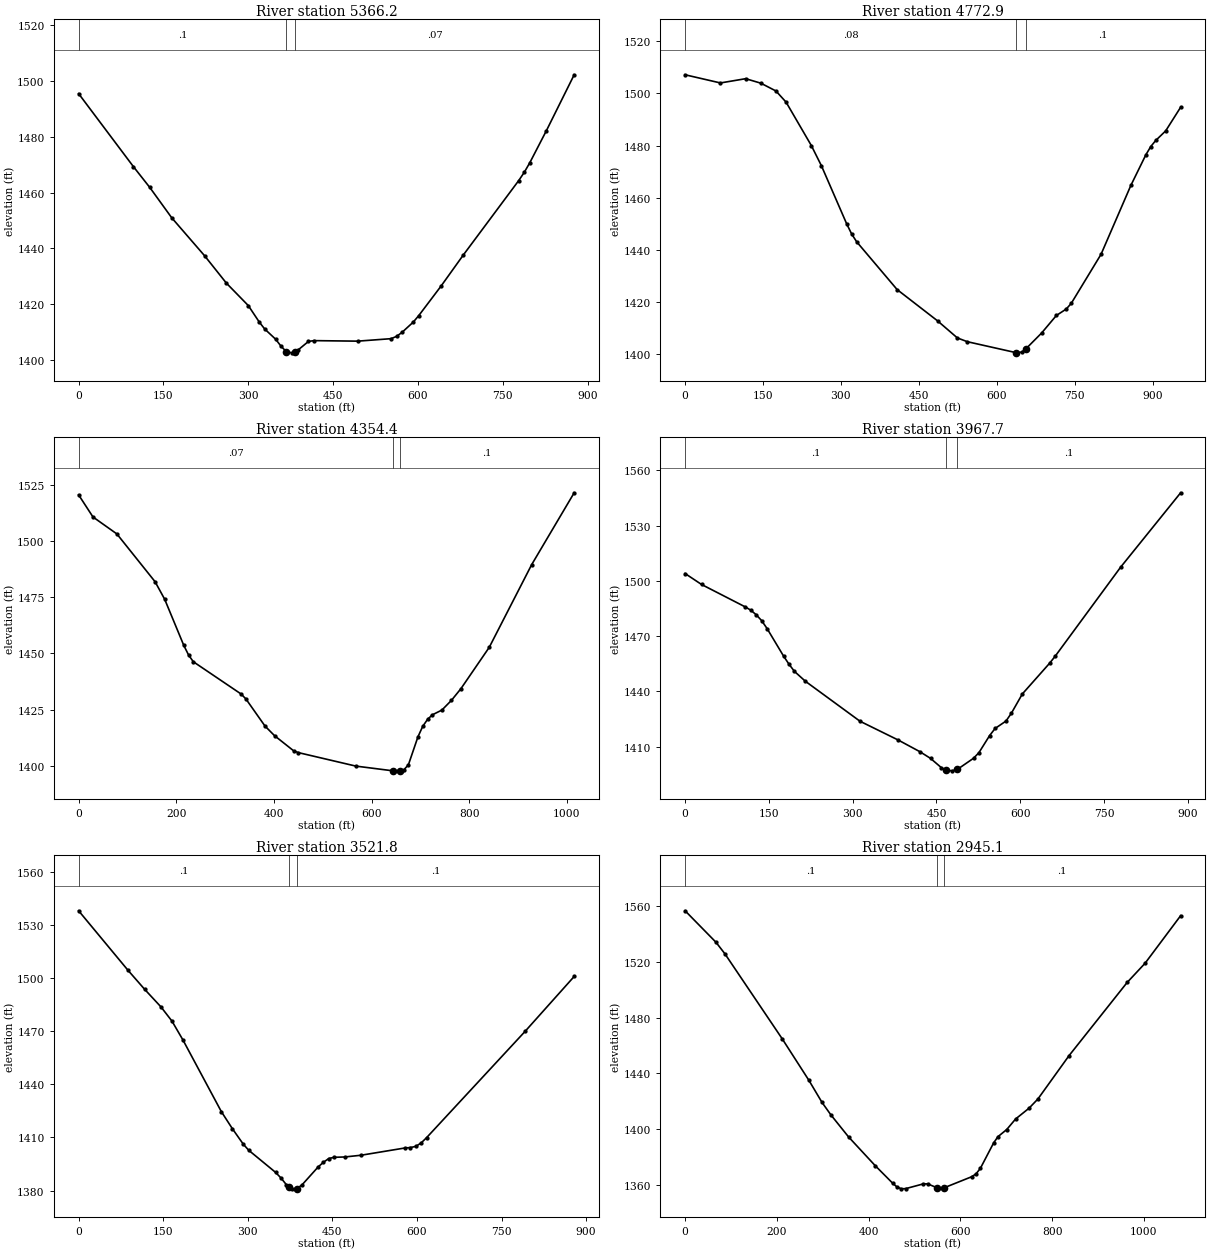
Type RM Length L Ch R = 1 ,5366.2  ,616.4,593.2,568.1
XS GIS Cut Line= 4
     1848432.359      293040.805     1848556.057      292767.368
     1848662.394      292617.628     1848571.248      292235.684
#Sta/Elev= 30
       0 1495.48    96.8 1469.33   125.8 1461.86   164.6 1450.98   222.7 1437.37
   261.4 1427.52   300.1 1419.48   319.4  1413.6   329.1 1411.08   348.4 1407.43
   358.1 1404.88   367.5 1402.95   377.4 1402.54   382.5 1402.99   387.1  1403.4
   406.4 1406.62   416.1 1406.92   493.6 1406.73   552.5 1407.62   562.3 1408.44
   572.1 1409.91   591.8 1413.56   601.6 1415.91   640.8 1426.43   680.1 1437.56
   778.3 1464.31   788.1 1467.26   797.9  1470.7   827.4 1482.26   876.4 1502.25
#Mann= 3 , 0 , 0
       0      .1       0   367.5    .045       0   382.5     .07       0
Bank Sta=367.5,382.5
XS Rating Curve= 0 ,0
Exp/Cntr=0.3,0.1

Type RM Length L Ch R = 1 ,4772.9  ,430.8,418.6,404.4
XS GIS Cut Line= 4
     1849148.505      292988.722     1848964.043      292528.653
     1848844.685      292300.788     1848705.796      292155.389
#Sta/Elev= 30
       0 1507.16      68 1504.03   116.6 1505.66   145.8 1503.94   174.9 1500.95
   194.4 1496.68     243 1480.05   262.4 1472.32     311 1450.07   320.7 1446.13
   330.4 1443.14   408.2 1424.85     486 1412.87   524.2 1406.32   543.3 1404.88
  637.34 1400.67   638.6 1400.61   648.1  1400.9   655.4 1402.01   686.2 1408.17
   714.8 1414.93   733.8  1417.4   743.4 1419.56   800.8 1438.38   858.2 1464.78
     887 1476.48   896.5 1479.66   906.1    1482   925.2 1485.66     954 1494.72
#Mann= 3 , 0 , 0
       0     .08       0  637.34    .045       0   655.4      .1       0
Bank Sta=637.34,655.4
XS Rating Curve= 0 ,0
Exp/Cntr=0.3,0.1

Type RM Length L Ch R = 1 ,4354.4  ,385.8,386.7,386.3
XS GIS Cut Line= 4
     1849673.678      292522.142     1849155.015      292246.535
     1848996.595      292148.878     1848781.751      292038.201
#Sta/Elev= 30
       0 1520.43    29.4 1510.61    78.3 1503.09   156.6 1481.84   176.2 1474.08
   215.4 1453.55   225.2 1449.28   234.9 1446.29   332.8 1431.94   342.6 1429.77
   381.8 1417.69   401.4 1413.41   440.5 1406.69   450.3 1405.89   567.8 1399.91
   643.8 1397.81   646.1  1397.8   658.8  1397.9   665.7 1398.14   675.5 1400.47
   695.1 1412.93   704.9 1417.58   714.7 1420.65   724.5 1422.69   744.1  1424.8
   763.6  1429.1   783.1 1434.31   841.1 1452.68   928.1 1489.46  1015.1 1521.37
#Mann= 3 , 0 , 0
       0     .07       0   643.8    .045       0   658.8      .1       0
Bank Sta=643.8,658.8
XS Rating Curve= 0 ,0
Exp/Cntr=0.3,0.1

Type RM Length L Ch R = 1 ,3967.7  ,449.4,445.9,443
XS GIS Cut Line= 4
     1849710.805       292233.14     1849412.194      291995.293
     1849271.569      291911.959     1848959.069       291773.07
#Sta/Elev= 30
       0 1503.98    29.4 1498.05   107.7 1485.88   117.5 1484.12   127.2 1481.64
     137 1478.46   146.8 1474.12   176.2 1459.26     186  1454.8   195.8  1450.9
   215.4 1445.54   313.2 1423.86   381.8 1413.64   420.2 1407.38   439.4 1403.73
   458.7 1398.72   466.9 1397.44   477.9 1396.97   487.5 1397.76   516.4 1403.79
     526  1406.8   545.2 1416.09     555 1419.95   574.5 1423.96   584.3 1428.29
   603.8 1438.67   652.7 1455.36   662.5  1459.1   779.7  1507.4   887.2 1547.77
#Mann= 3 , 0 , 0
       0      .1       0   466.9    .045       0   487.5      .1       0
Bank Sta=466.9,487.5
XS Rating Curve= 0 ,0
Exp/Cntr=0.3,0.1

Type RM Length L Ch R = 1 ,3521.8  ,580.9,576.7,570.4
XS GIS Cut Line= 4
     1849993.791      291924.112        1849749.      291731.404
      1849601.43      291668.904     1849219.685      291528.023
#Sta/Elev= 30
       0 1538.21    87.6 1504.53   116.8 1493.88     146 1483.84   165.5 1475.81
     185 1465.12   253.1 1424.59   272.6 1414.96   292.1 1406.14   301.8  1402.7
   349.2 1390.26   358.7 1387.12   368.1 1383.38  373.26 1382.05   377.5 1380.94
  387.39 1381.12   396.4 1383.28   424.7 1393.32   434.1 1395.97   443.5 1398.08
     453 1398.78   471.8 1398.96   500.9 1399.95   578.4 1404.04   588.1 1404.28
   597.8 1404.95   607.4 1406.91   617.1 1409.92   791.5 1469.94   878.7 1501.05
#Mann= 3 , 0 , 0
       0      .1       0  373.26    .045       0  387.39      .1       0
Bank Sta=373.26,387.39
XS Rating Curve= 0 ,0
Exp/Cntr=0.3,0.1

Type RM Length L Ch R = 1 ,2945.1  ,831.8,829.4,825.5
XS GIS Cut Line= 4
     1850143.296        291266.5      1849737.48      291184.035
     1849444.512      291138.462     1849075.588       291118.93
#Sta/Elev= 30
       0 1556.76    67.4 1534.12    86.7  1525.9   211.9 1464.71   269.6 1435.14
   298.5 1419.12   317.8  1410.2   356.3 1394.38   414.1 1373.84   452.4 1361.15
   461.9 1358.43   471.5 1357.12   481.1  1357.3   519.3 1360.68   528.9 1360.66
   548.5 1357.97   563.5 1357.74   624.5  1365.8   634.1 1367.88   643.6 1371.88
   672.4 1390.08   681.9 1394.59     701 1399.71   720.3 1407.27   749.5 1414.98
   768.9 1421.62     837 1452.85   963.4 1505.29  1002.3 1519.01    1080 1553.23
#Mann= 3 , 0 , 0
       0      .1       0   548.5    .045       0   563.5      .1       0
#XS Ineff= 2 , 0
          528.88 1360.66
Permanent Ineff=
       F       F
Bank Sta=548.5,563.5
XS Rating Curve= 0 ,0
Exp/Cntr=0.3,0.1

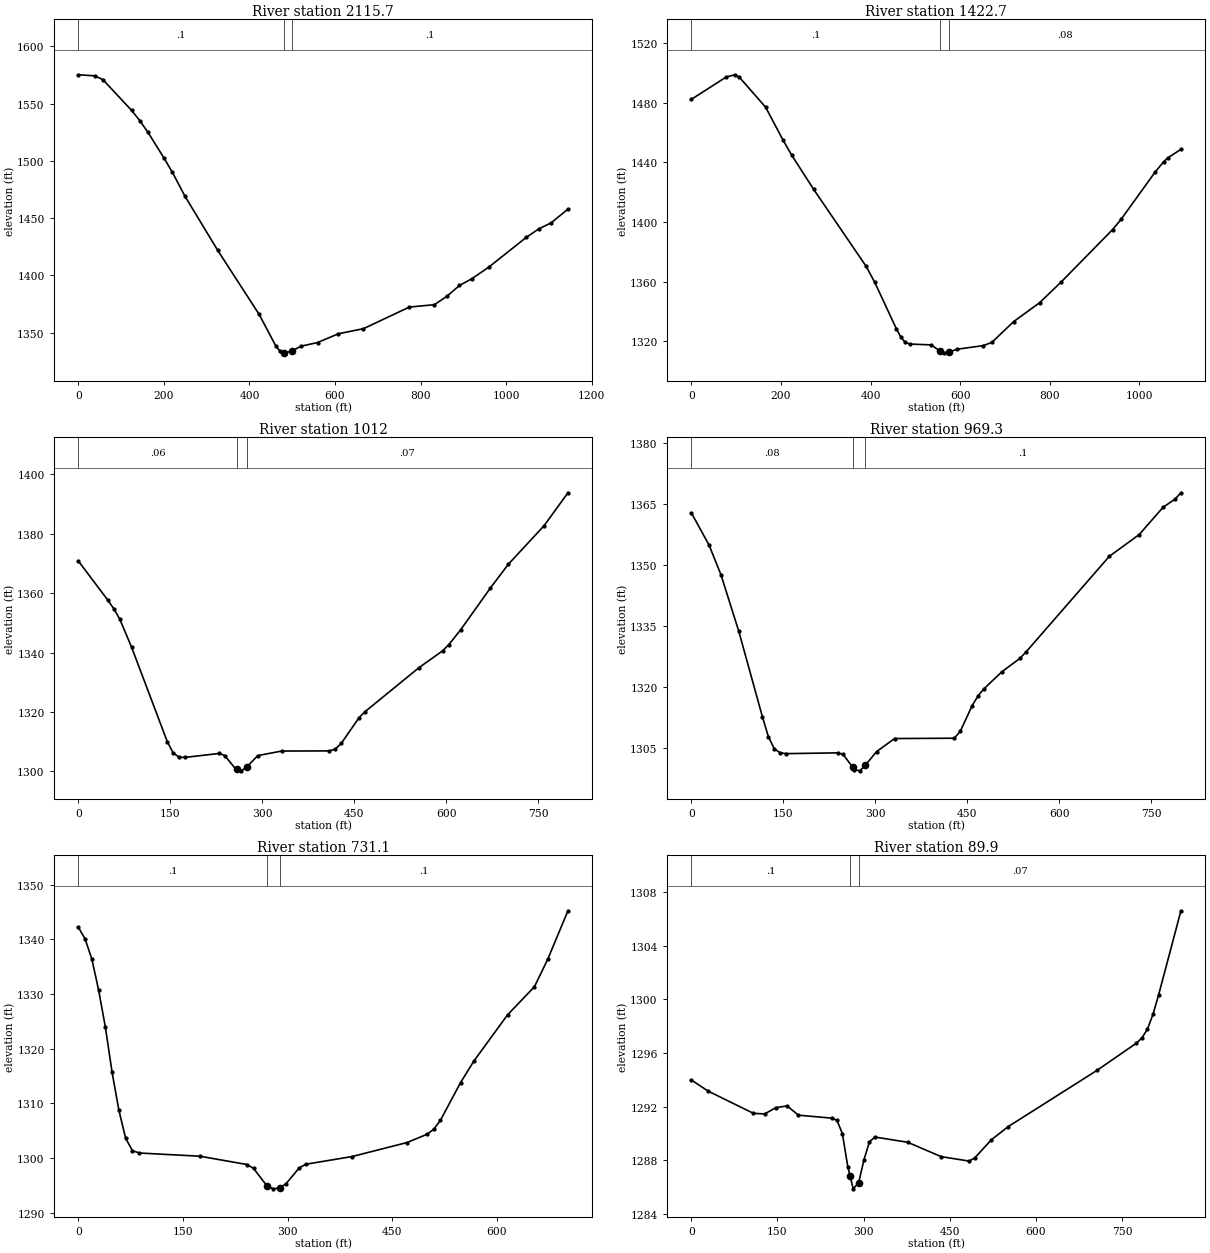
Type RM Length L Ch R = 1 ,2115.7  ,691,693.1,694.9
XS GIS Cut Line= 4
      1850329.06      290583.145     1850042.599      290570.189
     1849897.203      290563.614     1849185.397      290548.423
#Sta/Elev= 30
       0  1575.2    38.2 1574.28    57.4 1570.96   124.3  1544.2   143.4 1535.28
   162.5 1525.12   200.7 1502.19   219.8 1490.08   248.5 1469.65   325.6 1422.03
   422.6 1366.03   461.6 1338.46   471.3 1333.95   480.6 1332.56   481.1 1332.49
   498.2 1333.83   520.1 1338.26   559.1 1341.48   607.8 1349.14   666.4 1353.58
   773.6 1372.43   832.2 1374.53   861.4 1381.86   890.7 1391.27     920 1397.26
     959 1407.21  1046.7 1433.22    1076 1440.65  1105.2 1445.99  1144.3 1457.94
#Mann= 3 , 0 , 0
       0      .1       0   480.6    .045       0   498.2      .1       0
Bank Sta=480.6,498.2
XS Rating Curve= 0 ,0
Exp/Cntr=0.3,0.1

Type RM Length L Ch R = 1 ,1422.7  ,422.3,410.7,398.1
XS GIS Cut Line= 4
     1850299.546      289967.889     1849865.519      289905.389
     1849490.519      289863.722     1849213.959      289873.747
#Sta/Elev= 30
       0 1482.23      78 1497.28    97.4 1498.74   107.2 1497.09   165.7 1477.04
   204.6 1454.97   224.1 1444.78   272.8 1421.97   389.8 1370.39   409.3 1359.51
   457.8 1328.21   467.5 1322.71   477.2 1319.32   486.9 1318.13   535.2 1317.55
   554.6  1313.5   564.3 1312.22     574 1312.57   593.3 1314.66   651.3 1317.05
   670.7 1319.22   719.1 1333.13   777.1 1345.81   825.4 1359.76   939.9 1394.84
     959 1401.76  1035.3 1433.61  1054.4 1440.51  1063.9 1443.14  1092.6 1448.72
#Mann= 3 , 0 , 0
       0      .1       0   554.6    .045       0     574     .08       0
Bank Sta=554.6,574
XS Rating Curve= 0 ,0
Exp/Cntr=0.3,0.1

Type RM Length L Ch R = 1 ,1012    ,42.4,42.6,42.7
XS GIS Cut Line= 4
     1850001.803      289539.417     1849815.605      289458.687
     1849733.574      289495.146     1849247.897      289637.073
#Sta/Elev= 30
       0 1370.83    48.3 1357.59      58  1354.7    67.6 1351.26      87 1341.74
     145 1310.07   154.6 1306.27   164.3 1304.79     174 1304.72   229.9 1306.05
   238.8 1305.35   256.8 1300.77   258.6 1300.66   265.8  1300.2   274.8 1301.51
   292.7 1305.33   331.6 1306.86   409.5 1306.91   419.2 1307.51   428.9 1309.44
   458.1 1318.14   467.9 1320.15   555.4 1334.88   594.4 1340.61   604.1 1342.62
   623.6 1347.64   672.2 1361.74   701.4 1369.71   759.8 1382.71   798.7 1393.78
#Mann= 3 , 0 , 0
       0     .06       0   258.6    .045       0   274.8     .07       0
Bank Sta=258.6,274.8
XS Rating Curve= 0 ,0
Exp/Cntr=0.3,0.1

Type RM Length L Ch R = 1 ,969.3   ,217.5,238.2,258.6
XS GIS Cut Line= 4
     1850001.803      289495.146     1849815.605      289414.417
     1849733.574      289450.875     1849247.897      289592.802
#Sta/Elev= 30
       0 1362.92      29 1354.94    48.3 1347.67    77.3 1333.78     116 1312.62
   125.6 1307.78   135.3 1304.77     145 1303.75   154.6 1303.56   238.8 1303.75
   247.8 1303.35   263.4 1300.17   265.8 1299.65   274.8 1299.32   283.7 1300.69
   302.4 1304.08   331.6 1307.28   428.9 1307.36   438.7 1309.04   458.1 1315.39
   467.9 1317.84   477.6 1319.58   506.8 1323.76     536 1327.03   545.7 1328.57
   681.9 1352.19   730.6 1357.55   769.5 1364.26     789 1366.29   798.7 1367.85
#Mann= 3 , 0 , 0
       0     .08       0   263.4    .045       0   283.7      .1       0
Bank Sta=263.4,283.7
XS Rating Curve= 0 ,0
Exp/Cntr=0.3,0.1

Type RM Length L Ch R = 1 ,731.1   ,638.4,641.2,638.8
XS GIS Cut Line= 5
     1849995.614      289422.213     1849850.779      289240.301
     1849727.081      289174.112     1849635.935       289137.22
     1849406.986      289106.838
#Sta/Elev= 30
       0 1342.22     9.7 1340.09    19.4  1336.4    29.1 1330.71    38.8 1323.93
    48.4 1315.67    58.1 1308.76    67.8 1303.61    77.5 1301.35    87.2  1300.9
   174.4 1300.31   241.9 1298.79   251.2 1298.08   270.1 1294.95   279.3 1294.34
   288.6 1294.48     298  1295.3   316.7 1298.17   326.1 1298.84   392.5 1300.25
   471.2 1302.81     500 1304.32   509.6 1305.24   519.3  1306.9   548.1 1313.79
   567.4 1317.77   615.5 1326.19     654 1331.33   673.2 1336.39   702.1 1345.24
#Mann= 3 , 0 , 0
       0      .1       0   270.1    .045       0   288.6      .1       0
Bank Sta=270.1,288.6
XS Rating Curve= 0 ,0
Exp/Cntr=0.3,0.1

Type RM Length L Ch R = 1 ,89.9    ,89.9,89.9,89.9
XS GIS Cut Line= 4
     1850150.475      288919.077     1849985.198      288780.188
     1849856.725      288721.161     1849361.586        288728.8
#Sta/Elev= 30
       0 1293.98    29.4 1293.15   107.9  1291.5   127.6 1291.45   147.2 1291.92
   166.8 1292.05   186.4 1291.36   244.2 1291.14   253.6 1290.97     263 1289.99
   272.4 1287.53   276.4 1286.83   281.9 1285.87   291.4 1286.33   300.7 1288.05
   310.1 1289.37   319.6 1289.73   376.7 1289.34     435 1288.27   483.5 1287.94
   493.2 1288.16   522.3 1289.52   551.5  1290.5   706.8 1294.71   774.8 1296.72
   784.5 1297.11   794.2 1297.78   803.9 1298.88   813.6 1300.32   852.5 1306.59
#Mann= 3 , 0 , 0
       0      .1       0   276.4    .045       0   291.4     .07       0
#XS Ineff= 2 , 0
                          357.02         1289.38
Permanent Ineff=
       F       F
Bank Sta=276.4,291.4
XS Rating Curve= 0 ,0
Exp/Cntr=0.3,0.1

Chan Stop Cuts=-1
Use User Specified Reach Order=0
Composite Channel Slope=5